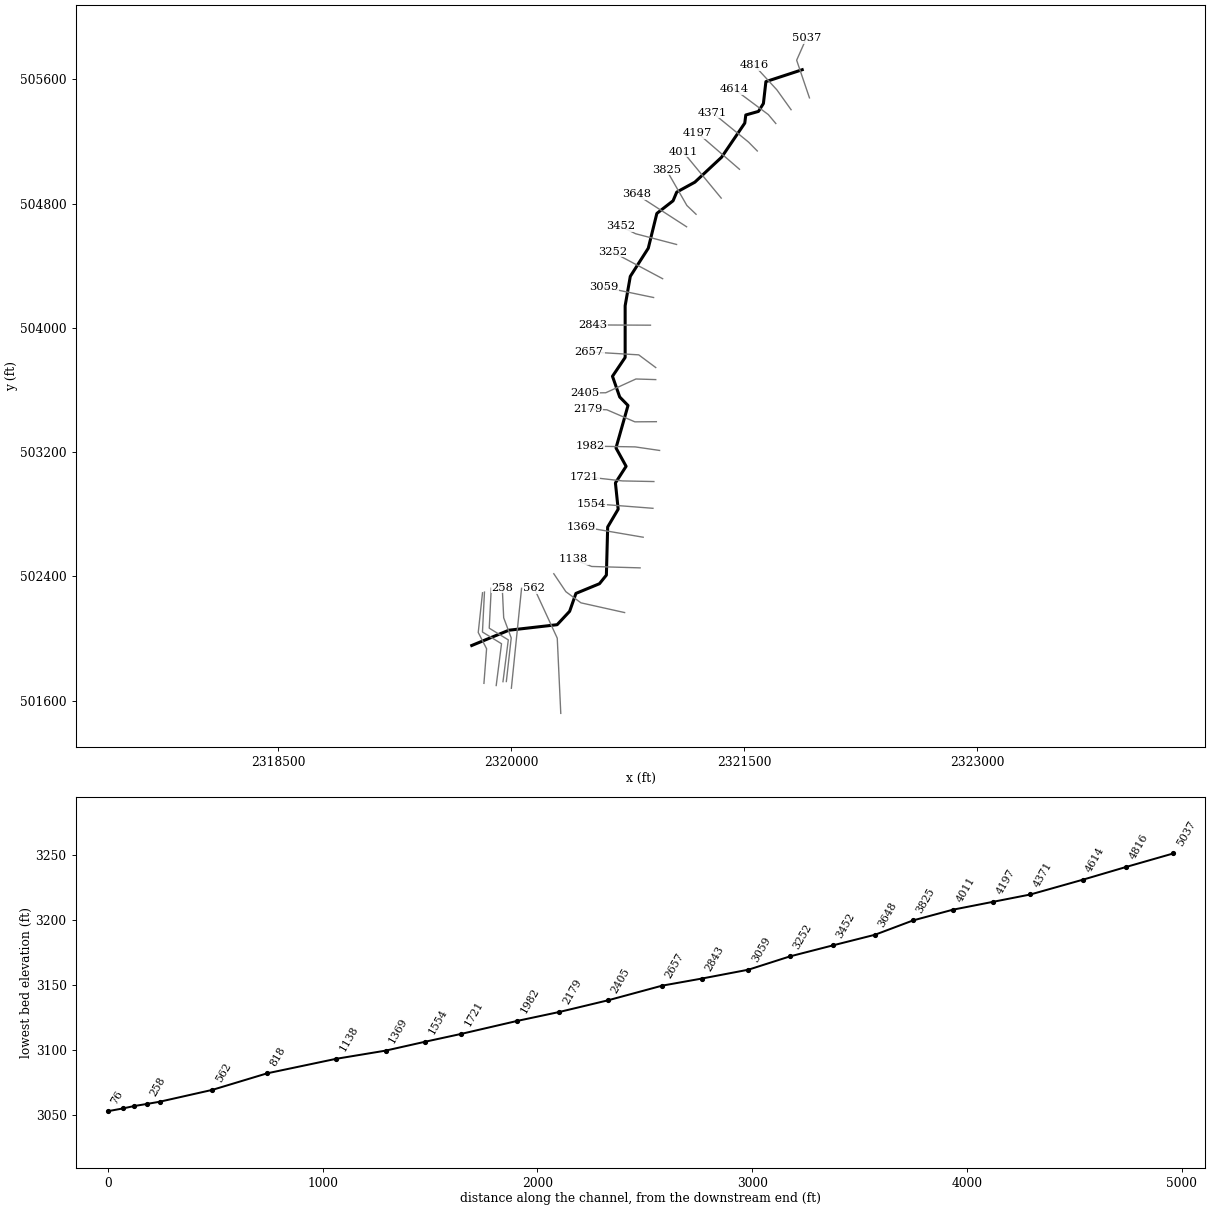
--- LPGALFRDRN.prj (project) ---

Proj Title=LPGALFRDRN
Current Plan=p01
Default Exp/Contr=0,0
English Units
Geom File=g01
Flow File=f01
Plan File=p01
Background Map Layer=Inundation Boundary (01pct Value_0)
BEGIN DESCRIPTION:
----------MODEL BY WOOD PLC 2021----------
Stream Name: Left Prong Galford Branch
Flood Zone: Approximate
Pocahontas County, WV
HEC-RAS Version: RAS 6.1
Vertical Datum: NAVD88
Projection: NAD 1983 StatePlane West Virginia S FIPS 4702 (US Feet)
Terrain: 1-meter LIDAR (FEMA Region III 3DEP collected 2016-2018)
Land Use: 2019 NLCD
Hydrologic Method:
WV SIR2010-5033 regression equations
Model Notes:
normal depth tie in with Galford Run
END DESCRIPTION:
DSS Export Rating Curves= 0
DSS Export Rating Curve Sorted= 0
DSS Export Volume Flow Curves= 0
DXF OffsetX= 0
DXF OffsetY= 0
DXF ScaleX= 0
DXF ScaleY= 0

--- LPGALFRDRN.p01 (plan) ---

Plan Title=Floodplain
Program Version=6.00
Short Identifier=Floodplain
Geom File=g01
Flow File=f01
Subcritical Flow
K Sum by GR= 0
Std Step Tol= 0.01
Critical Tol= 0.01
Num of Std Step Trials= 20
Max Error Tol= 0.3
Flow Tol Ratio= 0.001
Split Flow NTrial= 30
Split Flow Tol= 0.02
Split Flow Ratio= 0.02
Log Output Level= 0
Friction Slope Method= 1
Unsteady Friction Slope Method= 2
Unsteady Bridges Friction Slope Method= 1
Parabolic Critical Depth
Global Vel Dist= 0 , 0 , 0
Global Log Level= 0
CheckData=True
Encroach Param=-1 ,0,0, 0
Mapping Interval=1HOUR
Computation Time Step Use Courant=        0
Computation Time Step Use Time Series=    0
Computation Time Step Count To Double=0
Computation Time Step Max Doubling=0
Computation Time Step Max Halving=0
Computation Time Step Residence Courant=0
Run HTab= 0
Run UNet= 0
Run Sediment= 0
Run PostProcess= 0
Run WQNet= 0
Run RASMapper=-1
UNET Theta= 0
UNET Theta Warmup= 0
UNET ZTol= 0
UNET ZSATol= 0
UNET MxIter= 0
UNET Max Iter WO Improvement= 0
UNET MaxInSteps= 0
UNET DtIC= 0
UNET DtMin= 0
UNET MaxCRTS= 0
UNET WFStab= 0
UNET SFStab= 0
UNET WFX= 1
UNET SFX= 1
UNET Gravity=32.174
UNET 1D Methodology=Finite Difference
UNET DSS MLevel= 1
UNET Pardiso=0
UNET DZMax Abort= 0
UNET Use Existing IB Tables= 0
UNET Froude Reduction=False
UNET Froude Limit= 0
UNET Froude Power= 0
UNET D1 Cores= 0
UNET WindReference=Eulerian
UNET WindDragFormulation=Hsu (1988)
UNET D2 Coriolis=0
UNET D2 Cores= 0
UNET D2 Theta= 1
UNET D2 Theta Warmup= 1
UNET D2 Z Tol= 0.01
UNET D2 Volume Tol= 0.01
UNET D2 Max Iterations= 20
UNET D2 Equation= 0
UNET D2 RampUpFraction=0.1
UNET D2 TimeSlices= 1
UNET D2 Turbulence Formulation=Non-Conservative (original)
UNET D2 Eddy Viscosity=0.3
UNET D2 Transverse Eddy Viscosity=0.1
UNET D2 Smagorinsky Mixing=0
UNET D2 BCVolumeCheck=0
UNET D2 Cores=0
UNET D2 SolverType=PARDISO (Direct)
UNET D2 Minimum Iterations= 2147483647
UNET D2 Maximum Iterations= 2147483647
UNET D2 Restart Number= 10
UNET D2 Relaxation Coeff=1.3
UNET D2 SOR Precondition Iterations= 10
UNET D2 ILUT Maximum Fill= 8
UNET D2 ILUT Tolerance=1E-08
UNET D1D2 MaxIter= 0
UNET D1D2 ZTol=0.01
UNET D1D2 QTol=0.1
UNET D1D2 MinQTol=1
Write IC File= 0
Write IC File at Fixed DateTime=0
Write IC File at Sim End=0
Echo Input=False
Echo Parameters=False
Echo Output=False
Write Detailed= 0
HDF Write Warmup=0
HDF Write Time Slices=0
HDF Flush=0
HDF Compression= 1
HDF Chunk Size= 1
HDF Spatial Parts= 1
HDF Use Max Rows=0
HDF Fixed Rows= 1
Calibration Method= 0
Calibration Iterations= 20
Calibration Max Change=0.05
Calibration Tolerance=0.2
Calibration Maximum=1.5
Calibration Minimum=0.5
Calibration Optimization Method= 1
WQ AD Non Conservative
WQ ULTIMATE=-1
WQ Max Comp Step=1HOUR
WQ Output Interval=15MIN
WQ Output Selected Increments= 0
WQ Output face flow=0
WQ Output face velocity=0
WQ Output face area=0
WQ Output face dispersion=0
WQ Output cell volume=0
WQ Output cell surface area=0
WQ Output cell continuity=0
WQ Output cumulative cell continuity=0
WQ Output face conc=0
WQ Output face dconc_dx=0
WQ Output face courant=0
WQ Output face peclet=0
WQ Output face adv mass=0
WQ Output face disp mass=0
WQ Output cell mass=0
WQ Output cell source sink temp=0
WQ Output nsm pathways=0
WQ Output nsm derived pathways=0
WQ Create Restart=0
WQ Fixed Restart=0
WQ System Summary=0
WQ Write To DSS=0
Sorting and Armoring Iterations= 10
XS Update Threshold= 0.02
Bed Roughness Predictor= 0
Hydraulics Update Threshold= 0.02
Energy Slope Method= 1
Volume Change Method= 1
Sediment Retention Method= 0
Sediment TS Multiplier= 1
Warm Up Method= 0
XS Weighting Method= 0
Number of US Weighted Cross Sections= 1
Number of DS Weighted Cross Sections= 1
Upstream XS Weight=0
Main XS Weight=1
Downstream XS Weight=0
Number of DS XS's Weighted with US Boundary= 1
Upstream Boundary Weight= 1
Weight of XSs Associated with US Boundary= 0
Number of US XS's Weighted with DS Boundary= 1
Downstream Boundary Weight= 0.5
Weight of XSs Associated with DS Boundary= 0.5
Percentile Method= 0
Sediment Output Level= 3
Mass or Volume Output= 0
Output Increment Type= 1
Profile and TS Output Increment= 1
Transport Output Increment 1
XS Output Flag= 0
XS Output Increment= 10
Read HDF5 Sediment Hotstart= 0
Sediment Hotstart Type= 0
Write Gradation File= 0
Read Gradation Hotstart= 0
Write HDF5 File= 1
Write Binary Output= 1
Write DSS Sediment File= 0
DSS Sediment Output Type= 1
SV Curve= 0
Specific Gage Flag= 0
Subcell Erosion Methods= 0
Subcell Deposition Methods= 0
Advection Scheme= 1
Matrix Solver= 0
Implicit Weighting Factor= 1
Maximum Outer Loop Convergence Iterations= 5
Convergence Maximum Absolute= 0.001
Convergence RMSE= 0.0001
Grain Fractions Max Abs Error= 0.001
Max Subgrid Regions= 1
Max Subgrid Length Scale= 3.402823E+38
Initial Layer Thickness= 3.402823E+38
Min Layer Thickness= 3.402823E+38
Max Layer Thickness= 3.402823E+38
Number of Layers= 5

--- LPGALFRDRN.f01 (steady flow) ---

Flow Title=Flow
Program Version=6.10
Number of Profiles= 6
Profile Names=01pct,10pct,04pct,02pct,0_2pct,01plus
River Rch & RM=LPGALFRDRN,Main            ,5037
     610     323     429     517     851     902
Boundary for River Rch & Prof#=LPGALFRDRN,Main            , 1
Up Type= 0
Dn Type= 3
Dn Slope=0.02958
Boundary for River Rch & Prof#=LPGALFRDRN,Main            , 2
Up Type= 0
Dn Type= 3
Dn Slope=0.02958
Boundary for River Rch & Prof#=LPGALFRDRN,Main            , 3
Up Type= 0
Dn Type= 3
Dn Slope=0.02958
Boundary for River Rch & Prof#=LPGALFRDRN,Main            , 4
Up Type= 0
Dn Type= 3
Dn Slope=0.02958
Boundary for River Rch & Prof#=LPGALFRDRN,Main            , 5
Up Type= 0
Dn Type= 3
Dn Slope=0.02958
Boundary for River Rch & Prof#=LPGALFRDRN,Main            , 6
Up Type= 0
Dn Type= 3
Dn Slope=0.02958
DSS Import GetInterval= 0
DSS Import GetPeak= 0
DSS Import FillOption= 0

--- LPGALFRDRN.g01 (geometry) ---

Geom Title=Geometry
Program Version=6.10

River Reach=LPGALFRDRN      ,Main
Reach XY= 30
2321874.84566189505662.0756801372321640.92388564505585.400964722
2321624.92785464 505444.472112732321593.12608097505393.679891482
2321511.47106056505370.6451606452321504.89692672505318.196118563
2321355.76303864505098.7451138942321183.51403931 504937.99609156
2321066.71309181504873.9158391512321043.19607846504818.115097731
2320938.74714039504736.6388827262320883.58386488 504512.73086597
2320767.82687855504331.4280789792320734.70096055504142.436002895
2320734.67996322503809.3700679842320653.06989022503688.113092646
2320699.65116189503554.8971517242320753.08314164503500.142996147
2320675.74307323503226.6809446362320740.84136821503108.517467067
2320672.10102014 503001.478967222320689.73287463502832.224056393
2320622.13294423502717.6711358882320613.88492922502407.982122734
2320569.37189488502352.5849238042320417.71504597502290.109983146
 2320377.1711638502174.7709749792320296.72184964502088.647131473
2319985.84090972502053.0753522222319747.01067872 501954.77436772

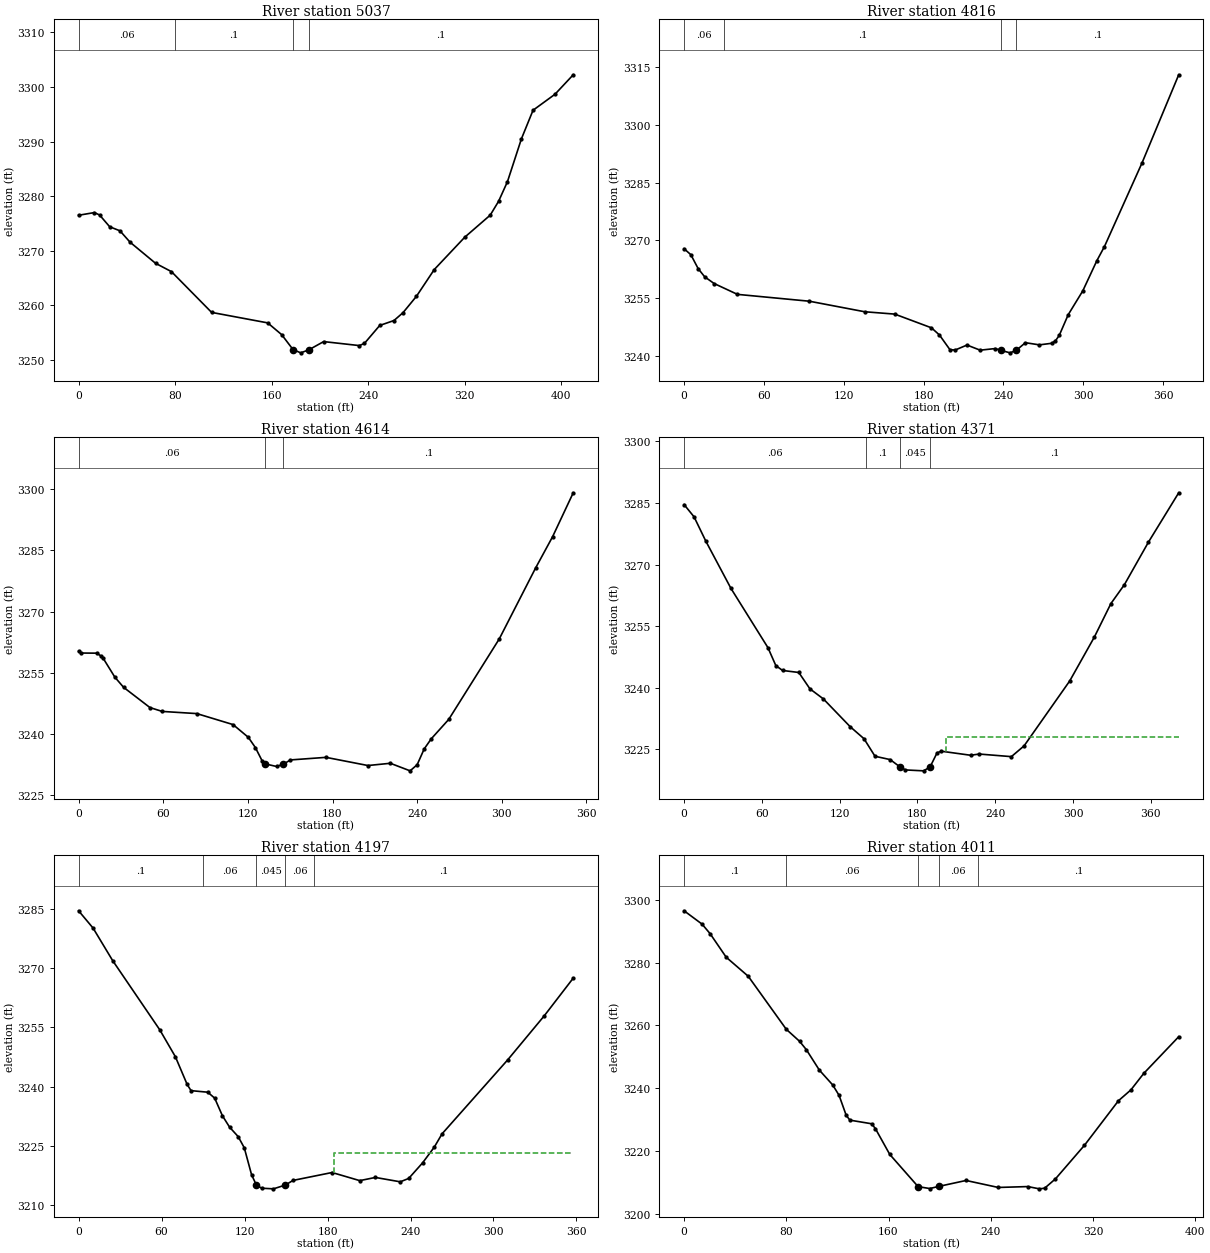
Type RM Length L Ch R = 1 ,5037    ,221,221,221
XS GIS Cut Line= 3
2321921.39066917505480.7513606362321838.96597936505723.214993225
2321901.21378455505864.119599714
#Sta/Elev= 30
       0 3276.49    13.1 3276.98    17.4 3276.54    25.8 3274.38    34.3 3273.64
    42.7 3271.55    63.8 3267.69      77 3266.16   110.3 3258.69   156.8 3256.77
   168.4 3254.61   177.8 3251.88   184.2 3251.28   190.8 3251.82   203.2 3253.34
   232.8 3252.61     237 3253.01   249.7  3256.3   261.5  3257.2     269 3258.64
   280.1 3261.63   294.9 3266.54   320.2 3272.47   341.3 3276.51   348.2 3279.03
   355.6 3282.65   367.2 3290.51   376.8 3295.73     395 3298.66410.1326 3302.23
#Mann= 4 ,-1,0
       0     .06       0      80      .1       0   177.8    .045       0
   190.8      .1       0
Bank Sta=177.8,190.8
XS Rating Curve= 0 ,0
Exp/Cntr(USF)=0,0
Exp/Cntr=0.3,0.1

Type RM Length L Ch R = 1 ,4816    ,198.4,201.8,202.3
XS GIS Cut Line= 3
2321803.12435946505404.5648829682321711.73180146505532.295103448
2321566.40900209505690.288794148
#Sta/Elev= 30
       0 3267.85     5.1  3266.3    10.6 3262.68    15.5 3260.56    22.6 3258.82
    40.1 3256.01    94.2 3254.23   135.7  3251.5   158.3 3250.89   185.9 3247.33
   191.9 3245.47   199.8 3241.65   203.7 3241.57   212.6 3242.86   222.5 3241.53
   233.8 3241.95237.95823241.489     245 3240.84  249.71 3241.51   256.5 3243.47
     267 3242.91   276.3 3243.32   279.1 3243.97   281.9 3245.35   288.7 3250.76
   299.6 3256.91   310.2 3264.76   315.9 3268.42   344.2 3290.17   371.7 3312.98
#Mann= 4 ,-1,0
       0     .06       0      30      .1       0237.9582    .045       0
  249.71      .1       0
Bank Sta=237.9582,249.71
XS Rating Curve= 0 ,0
Exp/Cntr=0.3,0.1

Type RM Length L Ch R = 1 ,4614    ,240.1,243.1,241.6
XS GIS Cut Line= 3
2321704.73530631505315.7705968592321656.37745238505373.277233963
2321435.49968714505537.955331123
#Sta/Elev= 30
       0 3260.32     1.8 3259.86    12.8 3259.83    15.6 3259.21    17.5 3258.54
    25.7 3253.96    31.9 3251.47    50.6 3246.51    59.3 3245.57    83.8 3245.04
   109.5 3242.35   120.3 3239.24   125.3 3236.74   130.3 3233.35   132.4 3232.72
   140.3  3232.1   145.2 3232.67   150.2  3233.7   175.4 3234.33   205.1 3232.33
     221 3232.88     235 3231.03     240 3232.52     245  3236.4     250 3238.87
   262.4 3243.62   298.2 3263.31   323.9 3280.63     336 3288.32350.6467 3299.08
#Mann= 3 ,-1,0
       0     .06       0   132.4    .045       0   145.2      .1       0
Bank Sta=132.4,145.2
XS Rating Curve= 0 ,0
Exp/Cntr(USF)=0,0
Exp/Cntr=0.3,0.1

Type RM Length L Ch R = 1 ,4371    ,172.5,173.9,172.3
XS GIS Cut Line= 3
2321585.60178122505138.8015506982321528.94797244505196.182931065
2321295.65400146505386.346924214
#Sta/Elev= 30
       0 3284.62     7.7 3281.63    16.8 3275.69    36.2 3264.17    64.7 3249.75
    70.8 3245.37      76 3244.19    88.5  3243.7    97.1 3239.71   107.5 3237.25
   128.1  3230.5   138.8 3227.56   147.3 3223.28     159 3222.47  166.34 3220.74
   170.8 3219.95   184.8 3219.73   189.8 3220.69   195.2 3224.13   198.5 3224.51
     221 3223.53   227.8 3223.82   252.5 3223.19   262.3 3225.81   297.5 3241.63
   316.5 3252.32   329.3  3260.5   339.7  3265.1   358.2 3275.44   381.6 3287.49
#Mann= 4 ,-1,0
       0     .06       0  140.64      .1       0  166.34    .045       0
   189.8      .1       0
#XS Ineff= 2 , 0
                          202.14         3227.99
Permanent Ineff=
       F       F
Bank Sta=166.34,189.8
XS Rating Curve= 0 ,0
Exp/Cntr=0.3,0.1

Type RM Length L Ch R = 1 ,4197    ,189,186.8,184.2
XS GIS Cut Line= 2
2321470.78785082505021.0490817042321200.24526263505254.996537193
#Sta/Elev= 30
       0 3284.59    10.5 3280.19    24.6 3271.98    58.7 3254.41      70 3247.58
    78.5 3240.56    81.3 3238.99    93.4 3238.59    98.4 3237.09     104 3232.62
   109.2 3229.72   115.4 3227.33   119.8  3224.5   125.1 3217.64   128.6 3215.02
   132.4 3214.25   140.9 3214.09   149.4 3215.04   155.1 3216.23   183.3 3218.23
   203.3 3216.17   214.6 3216.98   232.6 3215.87   238.7 3216.73   248.7 3220.66
   257.2 3224.67   262.8 3228.03   310.2 3246.76   336.6 3257.91357.6656 3267.51
#Mann= 5 ,-1,0
       0      .1       0      90     .06       0   128.6    .045       0
   149.4     .06       0     170      .1       0
#XS Ineff= 2 , 0
                          184.34         3223.17
Permanent Ineff=
       F       F
Bank Sta=128.6,149.4
XS Rating Curve= 0 ,0
Exp/Cntr(USF)=0,0
Exp/Cntr=0.3,0.1

Type RM Length L Ch R = 1 ,4011    ,187.4,185.4,183.1
XS GIS Cut Line= 2
2321353.16063856504835.4594801432321106.79697734505134.101902373
#Sta/Elev= 30
       0 3296.46    14.1 3292.21    20.4 3289.17      33 3281.68    50.2 3275.65
      80 3258.78    90.4 3254.96    95.7  3252.3   105.9 3245.79   116.3  3241.1
   121.3 3237.79   126.9 3231.42   129.8 3229.89   146.8 3228.74   149.7 3227.23
     161 3218.99   183.2 3208.74   192.3 3208.15   199.3 3208.82   220.7 3210.71
   245.9 3208.49     269 3208.77   278.1 3208.05   282.2 3208.25   290.7 3211.23
   313.4 3221.91     340 3236.07   349.7  3239.5   359.8 3244.76387.1464 3256.42
#Mann= 5 ,-1,0
       0      .1       0      80     .06       0   183.2    .045       0
   199.3     .06       0     230      .1       0
Bank Sta=183.2,199.3
XS Rating Curve= 0 ,0
Exp/Cntr(USF)=0,0
Exp/Cntr=0.3,0.1

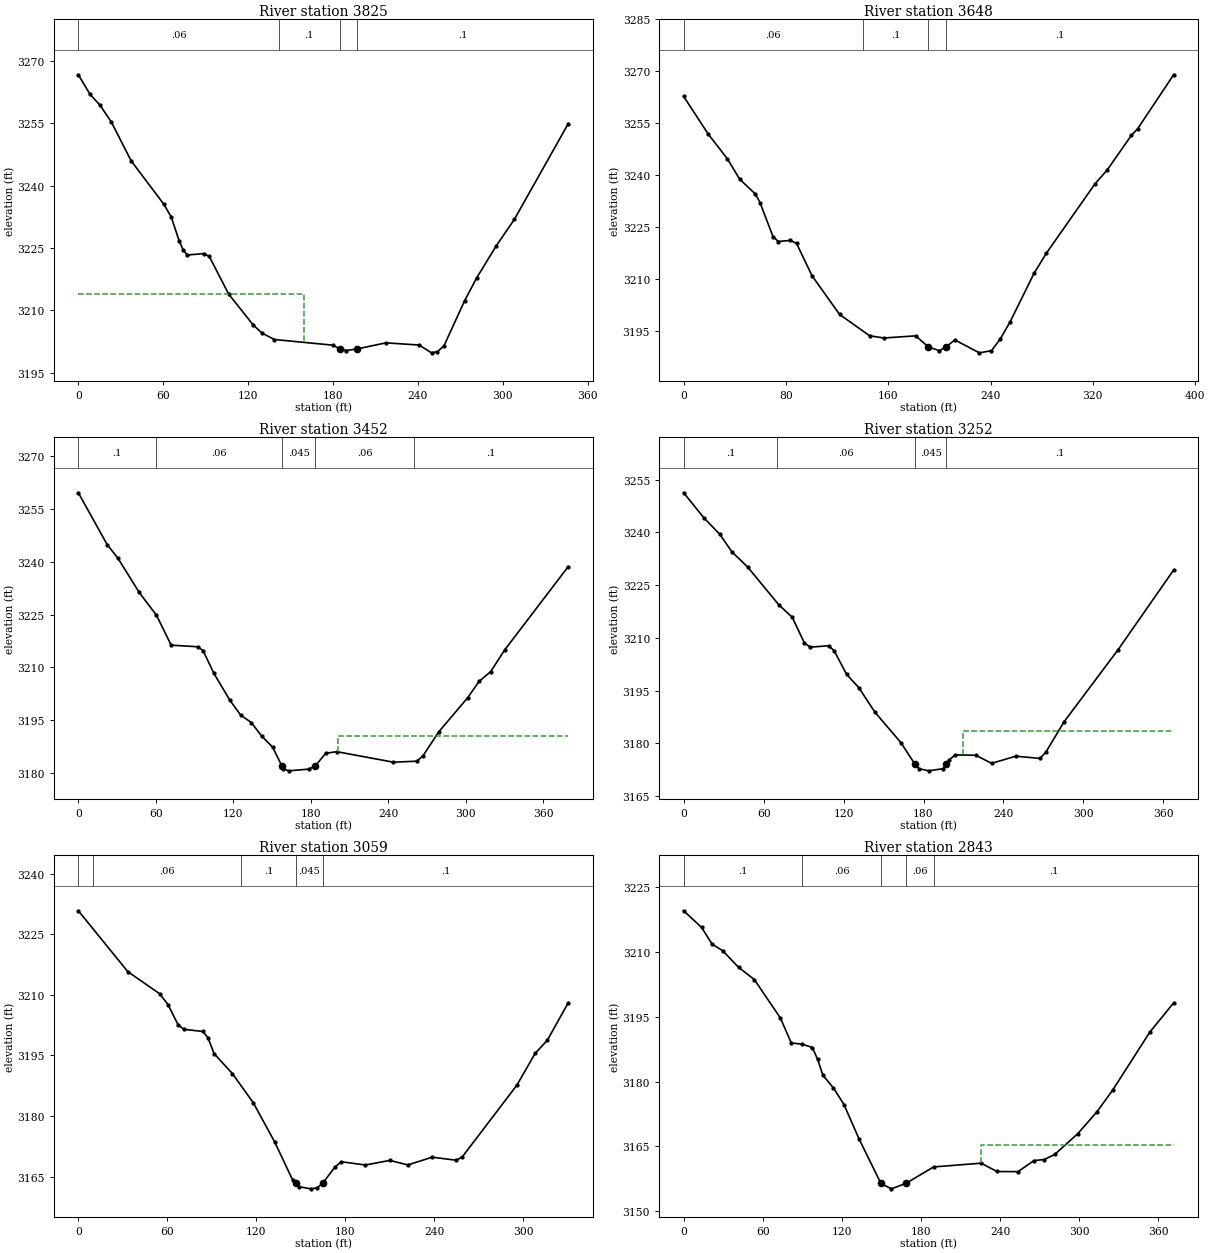
Type RM Length L Ch R = 1 ,3825    ,171.2,177.3,182.1
XS GIS Cut Line= 3
2321191.27127984504731.4227736392321132.10807294504787.896743859
2321000.33547576 505017.37827364
#Sta/Elev= 30
       0 3266.65     8.3 3261.93    15.3 3259.34    23.2 3255.38    37.3 3245.98
    60.5  3235.5    65.7 3232.43    71.3 3226.71    74.2  3224.5      77 3223.33
    88.5 3223.66    92.5 3223.02   106.3 3213.92   123.7 3206.48   129.9 3204.56
   138.6 3203.01   180.1 3201.65   184.7 3200.76   189.4 3200.36     197 3200.75
   217.5 3202.21   240.9 3201.69   249.7 3199.81   253.9 3200.12   258.5 3201.47
   273.1 3212.34   281.6  3217.8   295.4  3225.5   308.3  3231.9346.4138 3254.92
#Mann= 4 ,-1,0
       0     .06       0  141.79      .1       0   184.7    .045       0
     197      .1       0
#XS Ineff= 2 , 0
           159.3    3214
Permanent Ineff=
       F       F
Bank Sta=184.7,197
XS Rating Curve= 0 ,0
Exp/Cntr(USF)=0,0
Exp/Cntr=0.3,0.1

Type RM Length L Ch R = 1 ,3648    ,191.4,195.7,198.9
XS GIS Cut Line= 2
2321130.31524849504650.7456733262320808.50325946 504858.71330969
#Sta/Elev= 30
       0 3262.71    19.2 3251.87      34 3244.83    43.8 3238.87    56.1 3234.57
    59.7 3232.11    69.8 3222.34      74  3220.9    83.5 3221.22    88.3 3220.33
   100.3 3211.06   121.9 3199.88   145.4 3193.72   156.6 3193.08   181.4  3193.7
   191.4  3190.5     200 3189.42  204.96  3190.5   212.1 3192.51   231.2  3188.8
   240.7 3189.41   247.7 3192.87   255.1 3197.61     274 3211.72   283.5 3217.45
   321.5 3237.44   331.2 3241.52   350.2 3251.55     355  3253.4383.1625 3268.97
#Mann= 4 ,-1,0
       0     .06       0     140      .1       0   191.4    .045       0
  204.96      .1       0
Bank Sta=191.4,204.96
XS Rating Curve= 0 ,0
Exp/Cntr(USF)=0,0
Exp/Cntr=0.3,0.1

Type RM Length L Ch R = 1 ,3452    ,204.4,200.7,195.8
XS GIS Cut Line= 3
2321065.77356824504536.9013206612320802.22837388 504605.92506204
2320706.31226573504653.434910003
#Sta/Elev= 30
       0 3259.61    22.3  3244.9    30.6 3241.06    47.1 3231.33    60.5 3224.84
    71.9 3216.34    92.6 3215.88    96.6  3214.8     105 3208.31   117.4 3200.68
   125.7 3196.49     134 3194.36   142.2 3190.41   150.5 3187.39  157.49 3182.12
   158.8 3181.22   162.9 3180.65   178.5 3181.14   183.6 3182.09   191.6 3185.63
   200.1  3186.1     244 3183.11   262.2 3183.39     267 3184.94   279.2 3191.74
   301.5 3201.39   310.4 3206.06   319.4 3208.83   330.1 3214.93379.4719 3238.67
#Mann= 5 ,-1,0
       0      .1       0      60     .06       0  157.49    .045       0
   183.6     .06       0     260      .1       0
#XS Ineff= 2 , 0
                          201.46         3190.45
Permanent Ineff=
       F       F
Bank Sta=157.49,183.6
XS Rating Curve= 0 ,0
Exp/Cntr(USF)=0,0
Exp/Cntr=0.3,0.1

Type RM Length L Ch R = 1 ,3252    ,187.3,192.9,196.9
XS GIS Cut Line= 2
2320976.13234567504316.3839131372320651.63111996504489.391472698
#Sta/Elev= 30
       0 3251.24    15.3 3244.05    27.1 3239.44    36.2 3234.43    47.9 3230.17
    71.5 3219.33    81.5 3215.82    90.6 3208.52    95.1 3207.34   108.7 3207.72
   112.9 3206.34   122.3 3199.58   131.4 3195.83   143.6 3188.81   163.1 3180.14
  173.64    3174   176.7 3172.76   183.9 3172.15   194.9 3172.78   197.2 3174.07
   199.4 3175.36   203.9 3176.68   219.3 3176.58   231.1 3174.28   249.3 3176.32
   267.4 3175.68   271.9  3177.5   285.5  3186.1   325.8 3206.47367.7399 3229.27
#Mann= 4 ,-1,0
       0      .1       0      70     .06       0  173.64    .045       0
   197.2      .1       0
#XS Ineff= 2 , 0
                          209.58         3183.37
Permanent Ineff=
       F       F
Bank Sta=173.64,197.2
XS Rating Curve= 0 ,0
Exp/Cntr(USF)=0,0
Exp/Cntr=0.3,0.1

Type RM Length L Ch R = 1 ,3059    ,212.2,215.5,218.1
XS GIS Cut Line= 2
  2320917.865551504195.3682626672320594.26073752504262.599179595
#Sta/Elev= 30
       0 3230.83    33.4 3215.74    54.8 3210.29    60.5  3207.6    67.2 3202.65
    71.2 3201.47    84.1 3200.93    87.5 3199.32    91.6 3195.43   103.9 3190.52
     118 3183.29   132.5 3173.53   144.7 3164.04   146.6  3163.3   148.8 3162.48
     157 3161.96   161.1 3162.21   165.1 3163.48   173.3 3167.44   177.4 3168.67
   193.7 3167.86   210.1    3169   222.3 3167.88   238.7  3169.8     255 3169.04
   259.1 3169.92   295.9 3187.67   308.1 3195.49   316.3 3198.72330.5149 3208.06
#Mann= 5 ,-1,0
       0      .1       0      10     .06       0     110      .1       0
   146.6    .045       0   165.1      .1       0
Bank Sta=146.6,165.1
XS Rating Curve= 0 ,0
Exp/Cntr(USF)=0,0
Exp/Cntr=0.3,0.1

Type RM Length L Ch R = 1 ,2843    ,187.4,186.6,186.1
XS GIS Cut Line= 2
 2320897.7460766504017.1814324682320526.13340836504018.775054202
#Sta/Elev= 30
       0 3219.49    13.6 3215.63    21.6 3211.76    29.6 3210.25    41.6 3206.42
    53.6 3203.58    73.3 3194.72    81.6 3188.93      90 3188.64    97.6 3187.87
   101.6 3185.11   105.6 3181.46   113.6 3178.51   121.6 3174.68     133 3166.73
   149.6 3156.43   157.6 3155.19   168.8 3156.49   189.6 3160.26   225.6 3161.12
   237.6  3159.2   253.6 3159.16   265.6 3161.72   273.6 3161.97   281.6 3163.19
   298.9 3167.94   313.6 3173.06   325.6 3178.12   353.6 3191.45371.6161 3198.19
#Mann= 5 ,-1,0
       0      .1       0      90     .06       0   149.6    .045       0
   168.8     .06       0     190      .1       0
#XS Ineff= 2 , 0
                          225.35          3165.3
Permanent Ineff=
       F       F
Bank Sta=149.6,168.8
XS Rating Curve= 0 ,0
Exp/Cntr(USF)=0,0
Exp/Cntr=0.3,0.1

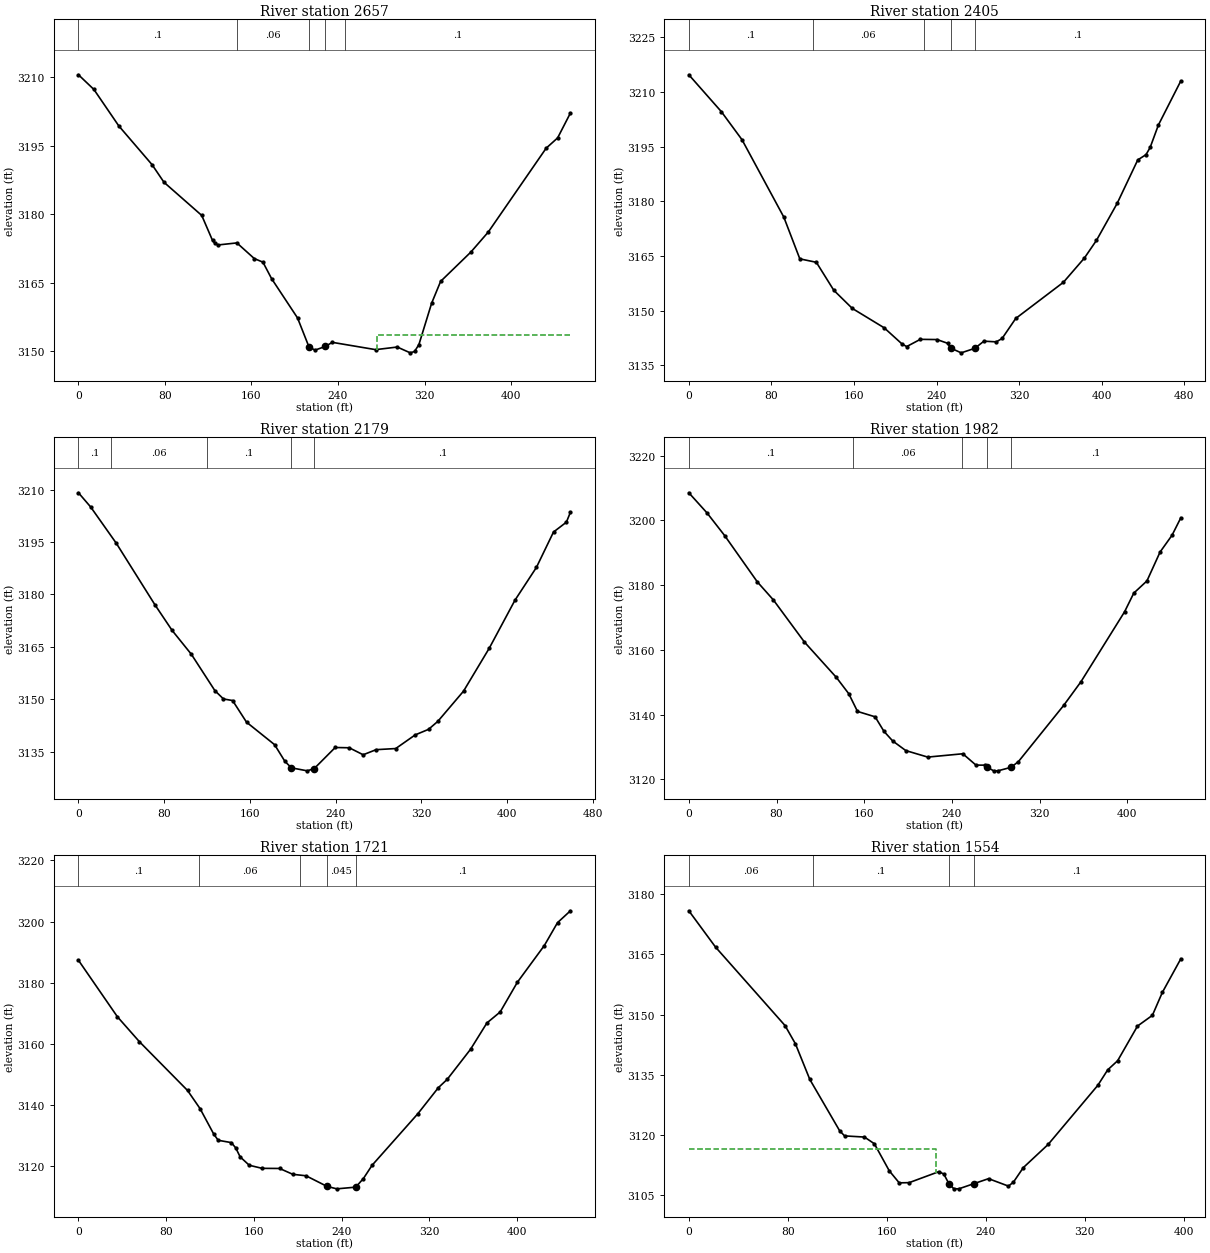
Type RM Length L Ch R = 1 ,2657    ,240.9,251.4,260.2
XS GIS Cut Line= 3
2320931.61053846503744.4729131362320822.04904421503826.146027034
2320504.32071087503845.070285132
#Sta/Elev= 30
       0 3210.59    14.3 3207.37    37.3 3199.39    68.1 3190.89    79.1 3187.04
     114 3179.78     124 3174.29   125.9 3173.75     129 3173.31   146.5 3173.76
   162.6 3170.33   170.6 3169.54   178.6 3165.93   202.6 3157.32   213.1 3151.02
   218.7 3150.27   228.3 3151.08   234.7 3151.98   274.8 3150.38   294.8 3150.95
   306.8 3149.68   310.8 3149.98   314.8 3151.48   326.6 3160.56   334.9 3165.33
   362.9 3171.76     379 3176.15   432.5 3194.51   443.1 3196.76454.9451 3202.22
#Mann= 5 ,-1,0
       0      .1       0  146.65     .06       0   213.1    .045       0
   228.3     .06       0  246.65      .1       0
#XS Ineff= 2 , 0
                          275.75         3153.63
Permanent Ineff=
       F       F
Bank Sta=213.1,228.3
XS Rating Curve= 0 ,0
Exp/Cntr(USF)=0,0
Exp/Cntr=0.3,0.1

Type RM Length L Ch R = 1 ,2405    ,236.7,226.2,210.5
XS GIS Cut Line= 4
2320931.61053846503666.7838535752320804.12079969503670.767907911
2320609.89815079503582.1226989252320474.44030335503580.130671757
#Sta/Elev= 30
       0 3214.67    31.5 3204.56    51.5 3196.87      92 3175.65   107.5 3164.21
   123.5 3163.27   140.4  3155.6   158.3 3150.63   189.2 3145.31   206.6 3140.85
     211 3140.17   224.2 3142.15   240.4 3142.09   250.6 3141.07   253.6 3139.75
   263.8 3138.45     277 3139.69   285.8 3141.65   297.8 3141.46   303.4 3142.39
   316.6 3147.87   362.8 3157.79   383.1 3164.43   394.8 3169.28   414.8 3179.39
   434.8 3191.33   442.8 3192.78   446.8 3194.75   454.8 3200.91   476.5 3212.98
#Mann= 5 ,-1,0
       0      .1       0     120     .06       0  227.55      .1       0
   253.6    .045       0     277      .1       0
Bank Sta=253.6,277
XS Rating Curve= 0 ,0
Exp/Cntr(USF)=0,0
Exp/Cntr=0.3,0.1

Type RM Length L Ch R = 1 ,2179    ,191.1,196.9,203.4
XS GIS Cut Line= 4
 2320935.5945928503395.868158695 2320797.1487046503394.872145111
2320616.87024588503472.5612046722320492.36854786503476.545259008
#Sta/Elev= 30
       0 3209.08    11.4 3205.02    35.4  3194.6    71.4 3177.02    87.4 3169.71
   105.4 3162.86   127.4 3152.44   135.4 3150.07   143.9 3149.62   156.9 3143.43
   183.1 3136.99   192.7 3132.23   198.8 3130.36   213.6  3129.5   220.1 3130.15
   239.7 3136.18   252.8  3136.1   265.8  3134.1   277.9 3135.56   296.2 3135.88
   314.4 3139.79   326.8 3141.37   335.5 3143.66   359.5 3152.31   383.5 3164.59
   407.5 3178.33   427.5  3187.7   443.5 3197.85   455.5 3200.66   459.3 3203.51
#Mann= 5 ,-1,0
       0      .1       0      30     .06       0     120      .1       0
   198.8    .045       0   220.1      .1       0
Bank Sta=198.8,220.1
XS Rating Curve= 0 ,0
Exp/Cntr(USF)=0,0
Exp/Cntr=0.3,0.1

Type RM Length L Ch R = 1 ,1982    ,258.9,260.4,257.7
XS GIS Cut Line= 3
2320956.51087806503210.6096320492320799.14073177503233.517944483
2320509.30077879503238.498012404
#Sta/Elev= 30
       0 3208.57    16.5 3202.38    32.7 3195.33    62.5 3181.02    77.1 3175.46
   105.4 3162.45   134.6 3151.49   145.9 3146.46   153.9 3140.97     170  3139.3
     178 3134.83     186 3131.84     198 3128.86     218 3126.85     250 3127.88
     262 3124.37     270 3124.36   272.3 3123.75     278 3122.62     282  3122.6
     294 3123.69   300.8 3125.48     342 3142.82   357.8 3150.15   397.6 3171.78
     406 3177.55     418 3181.32     430 3190.26   440.9 3195.44448.9115 3200.83
#Mann= 5 ,-1,0
       0      .1       0     150     .06       0  249.03      .1       0
   272.3    .045       0     294      .1       0
Bank Sta=272.3,294
XS Rating Curve= 0 ,0
Exp/Cntr(USF)=0,0
Exp/Cntr=0.3,0.1

Type RM Length L Ch R = 1 ,1721    ,165.1,167.1,167.6
XS GIS Cut Line= 3
2320919.65837545503010.4109016412320717.46761787503014.394955977
2320472.44827618503042.283336332
#Sta/Elev= 30
       0 3187.35    35.5  3168.9    55.5 3160.78    99.5  3144.8   110.9 3138.88
   123.5 3130.48   127.5 3128.51   139.5 3127.75   143.5    3126   147.5 3123.09
   155.8 3120.35   167.5 3119.34   183.5  3119.3   195.5 3117.39   207.6 3116.91
   226.8 3113.43   235.7 3112.64   252.9 3113.19   259.9 3115.99   267.9 3120.36
   309.6 3137.19   328.3  3145.7   336.4 3148.43   357.7 3158.27   372.6 3166.86
   384.7 3170.45   400.4 3180.17     425 3192.18     437 3199.64   448.8 3203.53
#Mann= 5 ,-1,0
       0      .1       0     110     .06       0  202.23      .1       0
   226.8    .045       0   252.9      .1       0
Bank Sta=226.8,252.9
XS Rating Curve= 0 ,0
Exp/Cntr(USF)=0,0
Exp/Cntr=0.3,0.1

Type RM Length L Ch R = 1 ,1554    ,186.9,184.9,184.9
XS GIS Cut Line= 2
2320913.68229395502838.1005515882320517.26888747502868.976972696
#Sta/Elev= 30
       0 3175.82   21.57 3166.79   77.74 3147.27   86.16 3142.72    97.8 3133.85
  121.88  3121.1  125.89 3119.82  141.94 3119.53  149.96 3117.86     162 3111.13
  170.02 3108.14  178.05 3108.19  202.12 3110.93  206.13 3110.31   210.13107.964
  214.15 3106.67  218.17 3106.65   230.2 3107.92  242.24 3109.18  258.29 3107.33
   262.3  3108.3  270.32 3111.93  290.38 3117.69  330.51 3132.39  338.53 3136.25
  346.55 3138.52   362.6 3147.14  374.64 3149.81  382.66  3155.5  397.61 3163.87
#Mann= 4 ,-1,0
       0     .06       0     100      .1       0   210.1    .045       0
   230.2      .1       0
#XS Ineff= 2 , 0
          199.66 3116.68
Permanent Ineff=
       F       F
Bank Sta=210.1,230.2
XS Rating Curve= 0 ,0
Exp/Cntr(USF)=0,0
Exp/Cntr=0.3,0.1

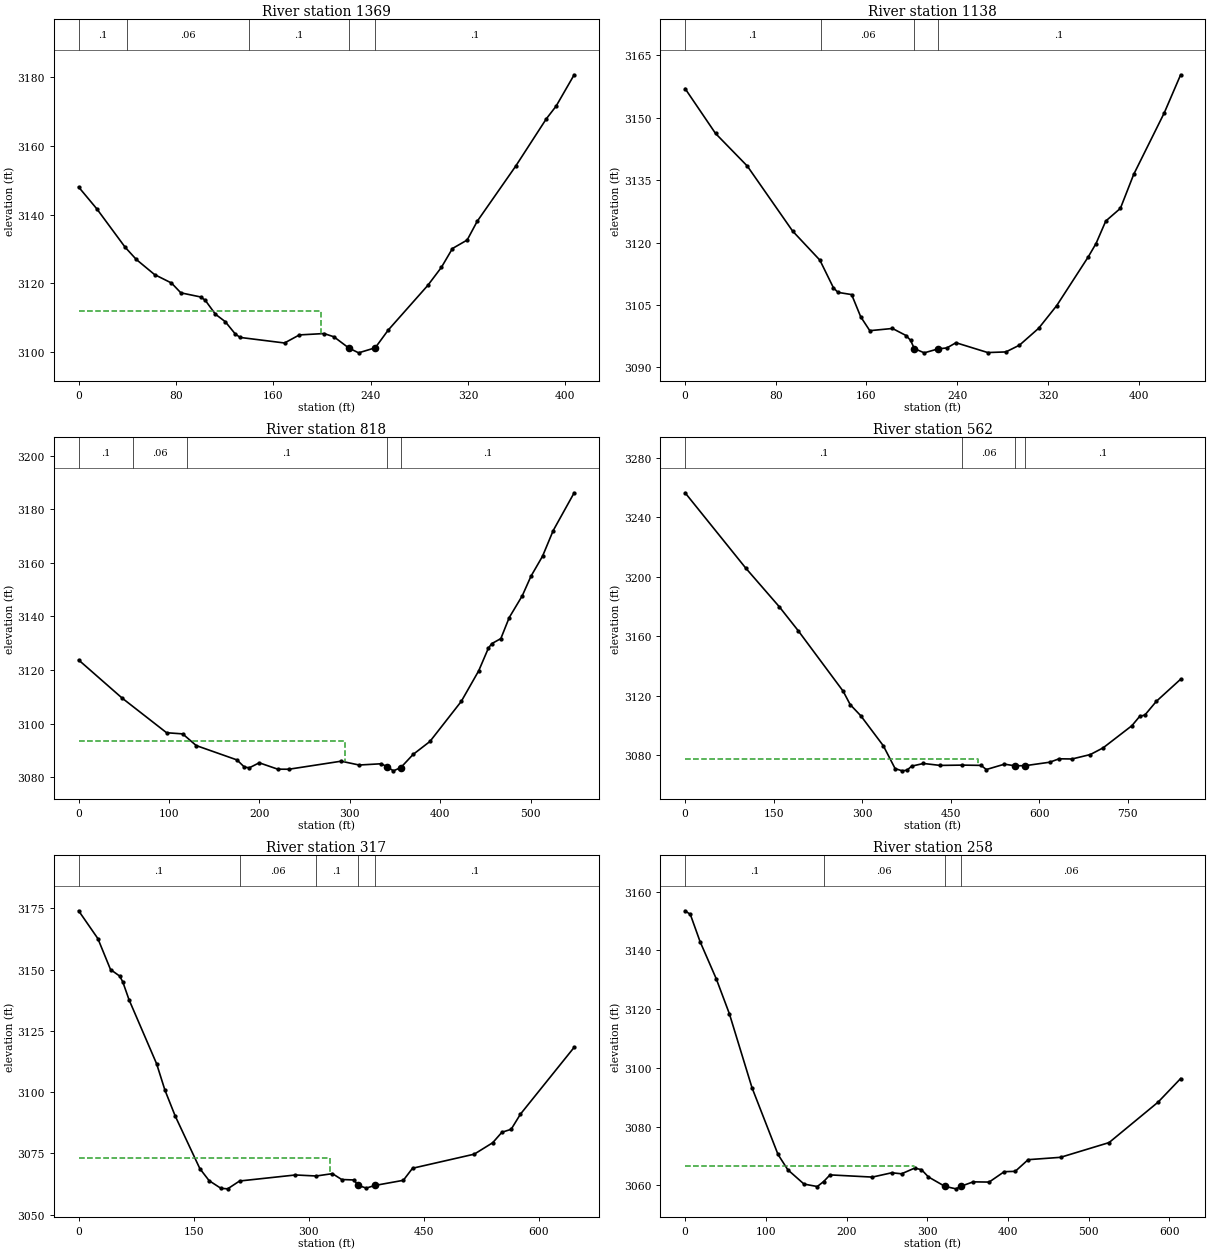
Type RM Length L Ch R = 1 ,1369    ,229,231.3,233.5
XS GIS Cut Line= 2
2320850.93343815502651.8460113582320449.53996375502720.570948662
#Sta/Elev= 30
       0 3148.09      15 3141.71    38.2 3130.56    47.4 3126.99    62.4 3122.59
    76.3 3120.13      84 3117.27   100.2 3116.07     104 3115.13   112.4 3111.05
   120.5 3108.87   128.6 3105.34   132.7 3104.28   169.2 3102.66   181.4 3105.01
   201.7 3105.41   209.8 3104.46   222.1 3101.18   230.1 3099.79  243.75 3101.26
   254.4 3106.41   286.9 3119.42   298.1 3124.68   307.2 3130.18   319.3 3132.65
   327.5 3138.08   359.2 3154.19   384.3 3167.94   392.4 3171.66407.2344 3180.79
#Mann= 5 ,-1,0
       0      .1       0      40     .06       0     140      .1       0
   222.1    .045       0  243.75      .1       0
#XS Ineff= 2 , 0
          199.44 3111.96
Permanent Ineff=
       F       F
Bank Sta=222.1,243.75
XS Rating Curve= 0 ,0
Exp/Cntr(USF)=0,0
Exp/Cntr=0.3,0.1

Type RM Length L Ch R = 1 ,1138    ,331.2,320,311
XS GIS Cut Line= 3
2320831.01316646502454.5608533052320519.26091463 502463.59944396
2320402.72732529502509.416068829
#Sta/Elev= 30
       0 3157.02   26.85 3146.23   54.86 3138.39   94.88 3122.74  118.89 3115.76
  130.89 3109.09  134.89 3108.01   146.9 3107.48   154.9 3102.14  162.91  3098.8
  182.92 3099.33  194.92 3097.63  198.92 3096.46  202.16  3094.5  210.93 3093.47
  222.93  3094.4  230.94 3094.66  238.94  3095.9  266.95 3093.54  282.96 3093.69
  294.96 3095.32  311.88 3099.38  327.82 3104.84  355.59 3116.54  362.48 3119.76
  371.07 3125.17  383.97 3128.22  395.69 3136.38  422.65 3151.18   437.1 3160.34
#Mann= 4 ,-1,0
       0      .1       0     120     .06       0  202.16    .045       0
  222.93      .1       0
Bank Sta=202.16,222.93
XS Rating Curve= 0 ,0
Exp/Cntr(USF)=0,0
Exp/Cntr=0.3,0.1

Type RM Length L Ch R = 1 ,818     ,260.4,255.6,246.6
XS GIS Cut Line= 4
2320731.11300398502166.7873958922320450.11041744502229.421295396
2320352.99969019502301.1539562232320275.23758653502416.786805506
#Sta/Elev= 30
       0 3123.73   48.09 3109.51   97.27 3096.58  115.05 3096.15  130.05 3091.79
  175.13 3086.43  183.33 3083.75  188.78  3083.5  199.72 3085.36  220.21 3082.98
  232.51 3082.96   290.3 3085.96   310.2 3084.53  334.62    3085 341.3523083.832
  348.08 3082.36 356.2543083.569  369.87 3088.48  388.48 3093.32  423.12 3108.27
   442.4 3119.68  453.12 3128.15  456.86 3129.83  466.89 3131.71  476.15 3139.55
  490.61 3147.71  500.25 3155.01     513 3162.45  524.79 3172.02  547.98 3186.12
#Mann= 5 ,-1,0
       0      .1       0      60     .06       0     120      .1       0
 341.352    .045       0 356.254      .1       0
#XS Ineff= 2 , 0
          294.02 3093.46
Permanent Ineff=
       F       F
Bank Sta=341.352,356.254
XS Rating Curve= 0 ,0
Exp/Cntr(USF)=0,0
Exp/Cntr=0.3,0.1

Type RM Length L Ch R = 1 ,562     ,248.7,245.7,232.5
XS GIS Cut Line= 3
2320320.21649776501517.6947339752320297.53043215502001.974069798
     2320148.875      502324.176
#Sta/Elev= 30
       0 3256.49   102.8 3205.86   159.7 3179.86   191.7 3163.79   267.8 3123.16
   279.8 3114.12   297.7 3106.65   335.9 3086.48   355.9 3071.12   367.9 3069.63
   375.9 3070.05   383.9 3072.77   403.9 3074.58     432 3073.28     470 3073.48
   501.6  3073.3   510.4  3070.5   541.2 3074.12   558.8 3073.02   576.4  3073.1
   617.9 3075.43   633.7 3077.72   655.7  3077.6   686.6 3080.57   708.3 3085.06
   757.1 3099.97   770.3 3106.24   779.1 3107.13   798.7 3116.41   839.7 3131.21
#Mann= 4 ,-1,0
       0      .1       0     470     .06       0   558.8    .045       0
   576.4      .1       0
#XS Ineff= 2 , 0
          496.11 3077.38
Permanent Ineff=
       F       F
Bank Sta=558.8,576.4
XS Rating Curve= 0 ,0
Exp/Cntr=0.3,0.1

Type RM Length L Ch R = 1 ,317     ,49.8,58.6,64.3
XS GIS Cut Line= 2
2320002.09005437501679.7860034942320067.74347165502322.946332079
#Sta/Elev= 30
       0    3174    25.1 3162.65    41.6 3150.02    53.7 3147.31    57.7 3144.89
    65.7 3137.73   101.7 3111.58   112.6 3100.78     126 3090.22   158.2 3068.72
   170.3 3063.82   185.6 3060.72   194.4  3060.5     2103063.701   282.9 3066.16
     3103065.742   331.1  3066.7   343.2 3064.31   359.3 3064.12   364.4 3061.93
   375.3 3060.81   386.3 3061.87   423.6 3063.98   435.6  3068.9   516.1 3074.65
   540.2 3079.32   552.2 3083.59   564.3 3084.81   576.4 3090.99   646.5 3118.27
#Mann= 5 ,-1,0
       0      .1       0     210     .06       0     310      .1       0
   364.4    .045       0   386.3      .1       0
#XS Ineff= 2 , 0
          327.32 3072.96
Permanent Ineff=
       F       F
Bank Sta=364.4,386.3
XS Rating Curve= 0 ,0
Exp/Cntr=0.3,0.1

Type RM Length L Ch R = 1 ,258     ,47.9,59.7,68.1
BEGIN DESCRIPTION:
Structure XS 4
END DESCRIPTION:
XS GIS Cut Line= 4
2319969.70478637501722.760785508 2320001.1689556502003.316294418
2319952.66169471502133.1059924662319943.48464535 502325.82402896
#Sta/Elev= 30
       0  3153.5     6.5 3152.25    18.5 3143.03    38.7 3130.27    54.8 3118.48
    82.9 3093.24   115.1 3070.53   127.2 3065.33   147.3 3060.45   163.7 3059.62
   171.5 3061.28   179.5 3063.58   231.9 3062.83     256  3064.3   268.1 3063.95
   284.3 3065.89   292.8 3065.36   301.4 3062.88   321.8 3059.67   335.5 3058.83
   342.3 3059.77   356.9 3061.21   376.6 3061.13   395.3 3064.67   408.9 3064.78
   424.9 3068.76     465 3069.56   525.1 3074.57   585.8 3088.33   613.8 3096.38
#Mann= 4 ,-1,0
       0      .1       0   171.5     .06       0   321.8    .045       0
   342.3     .06       0
#XS Ineff= 2 , 0
          283.39 3066.47     358            3060
Permanent Ineff=
       F       F
Bank Sta=321.8,342.3
XS Rating Curve= 0 ,0
Exp/Cntr(USF)=0,0
Exp/Cntr=0.5,0.3

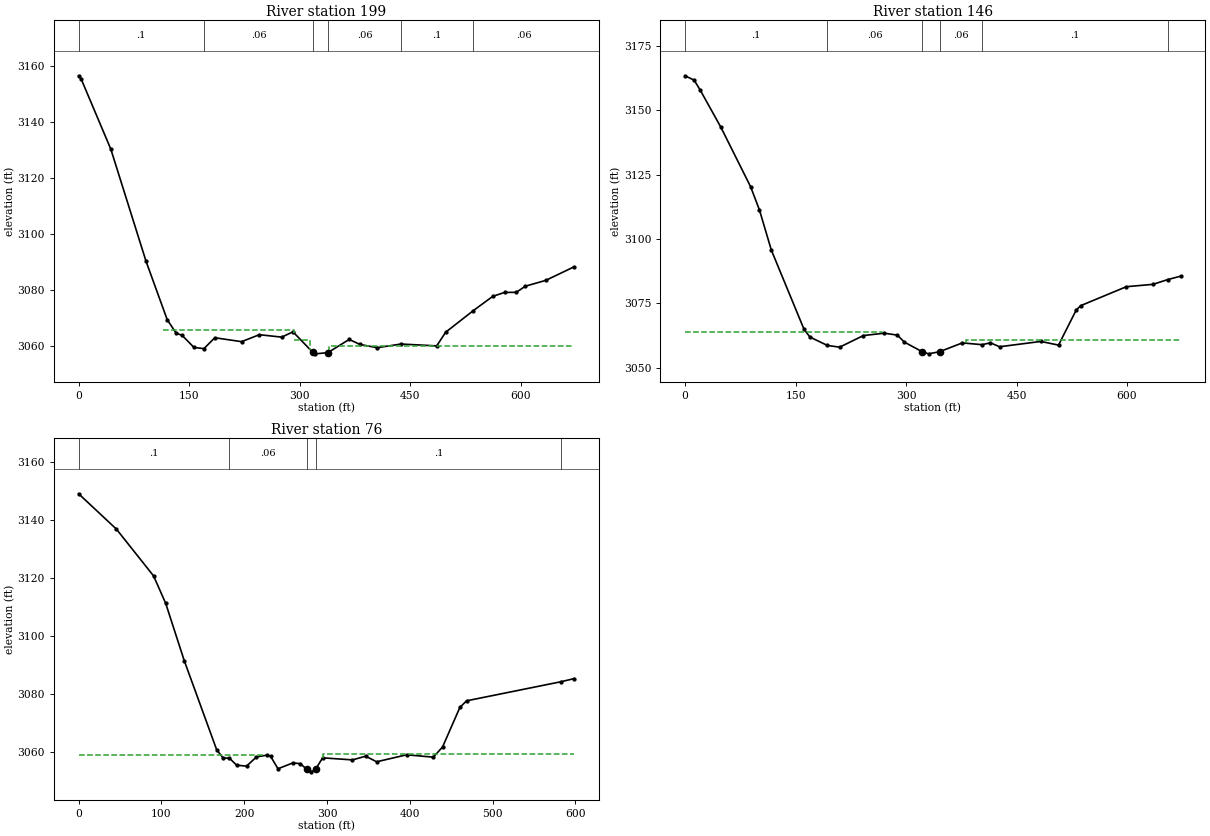
Type RM Length L Ch R = 1 ,199     ,51.8,52.6,55.5
BEGIN DESCRIPTION:
Structure XS 3
END DESCRIPTION:
XS GIS Cut Line= 4
2319948.10165611501721.7950103132319982.31894014501990.813657175
2319859.60868017502066.3276633122319872.58764997502323.547246715
#Sta/Elev= 30
       0  3156.5     3.4 3155.38    43.7  3130.3    91.6  3090.2   120.3 3069.38
   132.4  3064.6   140.5  3063.8   156.6 3059.51   170.1 3059.06   184.9 3062.96
   221.2 3061.56   245.3 3064.04   275.7 3063.18     291 3065.07   318.1  3057.7
   321.5 3057.21   338.4 3057.64   367.3 3062.35     382 3060.57   405.4  3059.4
   437.6 3060.71   486.2 3060.05   498.2  3064.9   535.8 3072.63   562.3 3077.74
   578.3 3079.14   594.3 3079.18   606.4 3081.35   634.4 3083.46   672.8  3088.3
#Mann= 6 ,-1,0
       0      .1       0   170.1     .06       0   318.1    .045       0
   338.4     .06       0   437.6      .1       0   535.8     .06       0
#XS Ineff= 4 ,-1
       0  114.42    3062  114.42  292.41 3065.75  292.41   314.3    3062
   339.7   672.8    3060
Permanent Ineff=
       F       F       F       F
Bank Sta=318.1,338.4
XS Rating Curve= 0 ,0
Exp/Cntr(USF)=0,0
Exp/Cntr=0.5,0.3

Type RM Length L Ch R = 1 ,146     ,81.1,70,59.4
BEGIN DESCRIPTION:
Structure XS 2
END DESCRIPTION:
XS GIS Cut Line= 4
2319904.44512131 501697.016977052319938.66240534501966.035623912
2319815.95214537502041.5496300482319828.93111518502298.769213452
#Sta/Elev= 30
       0 3163.42    12.3  3161.7    20.3 3157.97    48.6 3143.41    88.9 3120.33
     101 3111.23   117.1 3095.67   161.5 3064.88   169.5 3061.89   193.1 3058.64
   209.8 3057.96   242.1 3062.48   270.3 3063.39   288.2 3062.65   297.6 3059.95
   321.8  3056.2   330.5 3055.37   345.53056.199   376.4 3059.62   403.2 3058.93
   414.6 3059.65   426.9 3058.12     483 3060.19     507 3058.76     531 3072.37
   537.1 3074.09   599.1 3081.46   635.2 3082.37   655.3 3084.23   672.8 3085.55
#Mann= 6 ,-1,0
       0      .1       0   193.1     .06       0   321.8    .045       0
   345.5     .06       0   403.2      .1       0   655.3     .06       0
#XS Ineff= 2 , 0
           266.7 3063.81  381.64         3060.72
Permanent Ineff=
       F       F
Bank Sta=321.8,345.5
XS Rating Curve= 0 ,0
Exp/Cntr(USF)=0,0
Exp/Cntr=0.5,0.3

Type RM Length L Ch R = 1 ,76      ,,,
BEGIN DESCRIPTION:
Structure XS 1
END DESCRIPTION:
XS GIS Cut Line= 4
2319825.49401077501710.9617220492319842.53710243501933.832920716
2319788.78581334502038.7134847952319816.31696141502294.359859737
#Sta/Elev= 30
       0 3148.95    45.6 3136.79    90.5 3120.68   105.2  3111.2   127.5 3091.55
   166.7 3060.84   174.7 3057.93   181.9    3058   190.8 3055.53   202.8 3055.19
   214.8 3058.37   227.3 3058.96   231.8 3058.59   240.8 3054.29   258.7  3056.3
   267.7 3056.05   275.3 3054.16   281.2 3053.23  286.13 3054.12   294.7 3058.05
   330.7 3057.34   346.7 3058.62   359.9 3056.69   396.2  3059.1   428.3 3058.28
   439.5 3061.76   460.5 3075.43   468.6 3077.68   582.8 3084.26   598.5 3085.33
#Mann= 5 ,-1,0
       0      .1       0   181.9     .06       0   275.3    .045       0
  286.13      .1       0   582.8     .06       0
#XS Ineff= 2 , 0
          223.11 3059.11  295.59         3059.28
Permanent Ineff=
       F       F
Bank Sta=275.3,286.13
XS Rating Curve= 0 ,0
Exp/Cntr(USF)=0,0
Exp/Cntr=0.3,0.1
LCMann Table=0

Chan Stop Cuts=-1
Use User Specified Reach Order=0
Composite Channel Slope=5